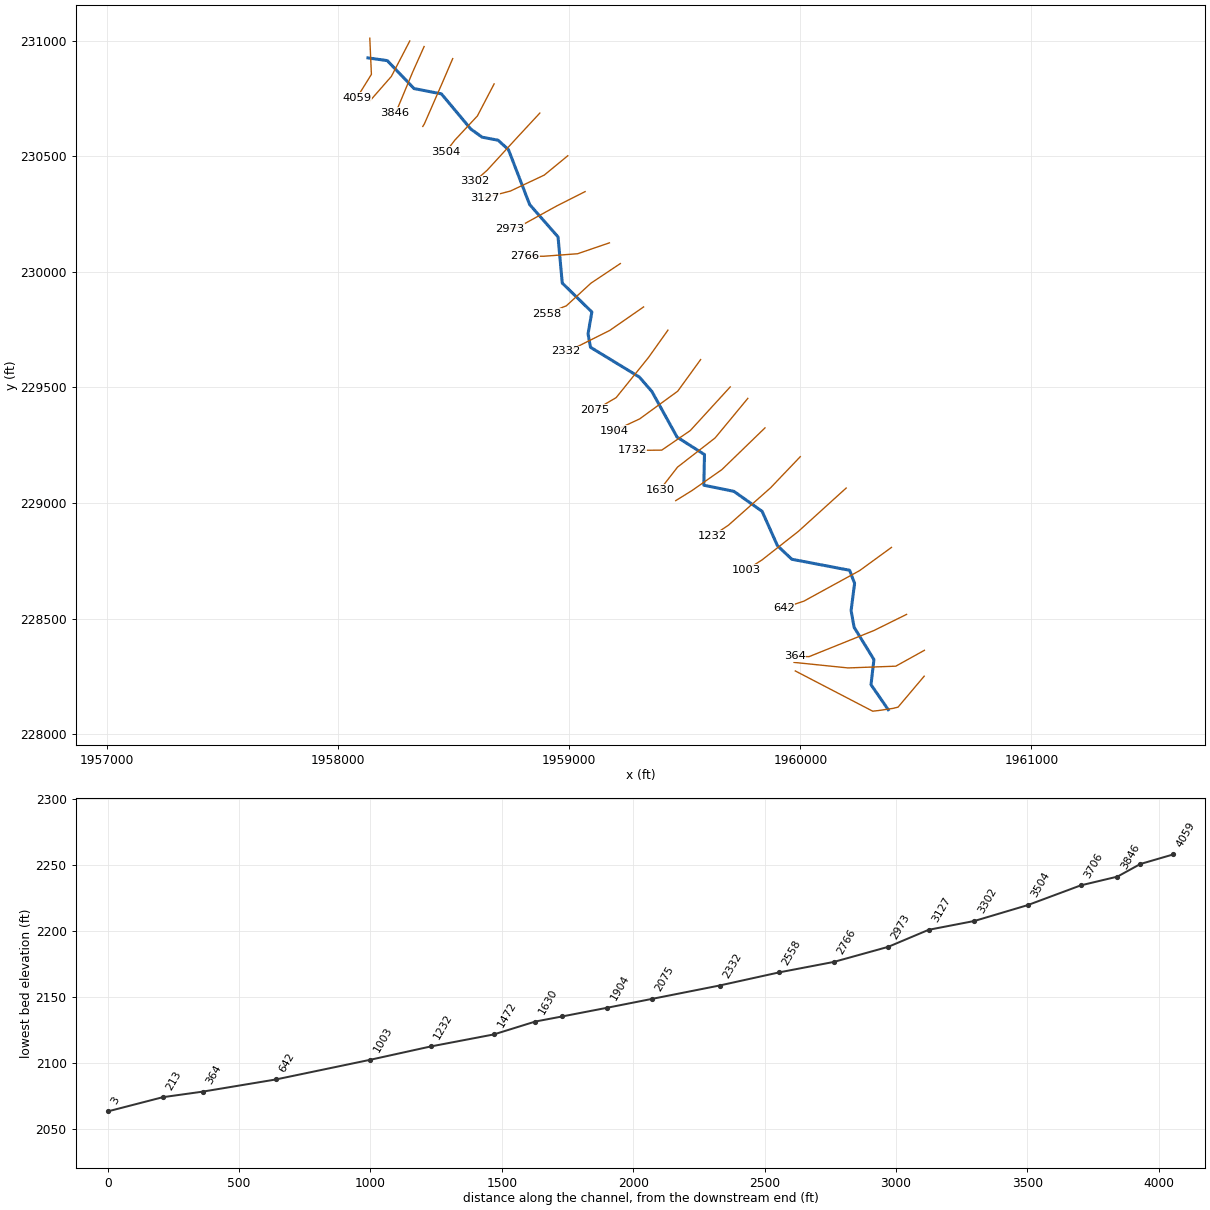
--- SPICELKCK.prj (project) ---

Proj Title=SPICELKCK
Current Plan=p01
Default Exp/Contr=0,0
English Units
Geom File=g01
Flow File=f01
Plan File=p01
Background Map Layer=QC
BEGIN DESCRIPTION:
Stream Name: Spicelick Creek
Flood Zone: Approximate
Summers County, West Virginia
HEC-RAS Version: 5.0.7
Hydrology Method:
Regression.
Model Notes:
END DESCRIPTION:
DSS Export Rating Curves= 0
DSS Export Rating Curve Sorted= 0
DSS Export Volume Flow Curves= 0
DXF OffsetX= 0
DXF OffsetY= 0
DXF ScaleX= 0
DXF ScaleY= 0

--- SPICELKCK.p01 (plan) ---

Plan Title=Floodplain
Program Version=5.07
Short Identifier=Floodplain
Geom File=g01
Flow File=f01
Subcritical Flow
K Sum by GR= 0
Std Step Tol= 0.01
Critical Tol= 0.01
Num of Std Step Trials= 20
Max Error Tol= 0.3
Flow Tol Ratio= 0.001
Split Flow NTrial= 30
Split Flow Tol= 0.02
Split Flow Ratio= 0.02
Log Output Level= 0
Friction Slope Method= 1
Unsteady Friction Slope Method= 2
Unsteady Bridges Friction Slope Method= 1
Parabolic Critical Depth
Global Vel Dist= 0 , 0 , 0
Global Log Level= 0
CheckData=True
Encroach Param=-1 ,0,0, 0
Mapping Interval=1HOUR
Computation Time Step Use Courant=        0
Computation Time Step Use Time Series=    0
Computation Time Step Count To Double=0
Computation Time Step Max Doubling=0
Computation Time Step Max Halving=0
Computation Time Step Residence Courant=0
Run HTab= 0
Run UNet= 0
Run Sediment= 0
Run PostProcess= 0
Run WQNet= 0
Run RASMapper= 0
UNET Theta= 0
UNET Theta Warmup= 0
UNET ZTol= 0
UNET ZSATol= 0
UNET MxIter= 0
UNET Max Iter WO Improvement= 0
UNET MaxInSteps= 0
UNET DtIC= 0
UNET DtMin= 0
UNET MaxCRTS= 0
UNET WFStab= 0
UNET SFStab= 0
UNET WFX= 1
UNET SFX= 1
UNET 1D Methodology=Finite Difference
UNET DSS MLevel= 1
UNET Pardiso=0
UNET DZMax Abort= 0
UNET Use Existing IB Tables= 0
UNET Froude Reduction=False
UNET Froude Limit= 0
UNET Froude Power= 0
UNET D1 Cores= 0
UNET D2 Coriolis=0
UNET D2 Cores= 0
UNET D2 Theta= 1
UNET D2 Theta Warmup= 1
UNET D2 Z Tol= 0.01
UNET D2 Volume Tol= 0.01
UNET D2 Max Iterations= 20
UNET D2 Equation= 0
UNET D2 RampUpFraction=0.1
UNET D2 TimeSlices= 1
UNET D2 BCVolumeCheck=0
UNET D1D2 MaxIter= 0
UNET D1D2 ZTol=0.01
UNET D1D2 QTol=0.1
UNET D1D2 MinQTol=1
Write IC File= 0
Write IC File at Fixed DateTime=0
Write IC File at Sim End=0
Echo Input=False
Echo Parameters=False
Echo Output=False
Write Detailed= 0
HDF Write Warmup=0
HDF Write Time Slices=0
HDF Flush=0
HDF Face Node Velocities=0
HDF Compression= 1
HDF Chunk Size= 1
HDF Spatial Parts= 1
HDF Use Max Rows=0
HDF Fixed Rows= 1
Calibration Method= 0
Calibration Iterations= 20
Calibration Max Change=0.05
Calibration Tolerance=0.2
Calibration Maximum=1.5
Calibration Minimum=0.5
Calibration Optimization Method= 1
WQ AD Non Conservative
WQ ULTIMATE=-1
WQ Max Comp Step=1HOUR
WQ Output Interval=15MIN
WQ Output Selected Increments= 0
WQ Output face flow=0
WQ Output face velocity=0
WQ Output face area=0
WQ Output face dispersion=0
WQ Output cell volume=0
WQ Output cell surface area=0
WQ Output cell continuity=0
WQ Output cumulative cell continuity=0
WQ Output face conc=0
WQ Output face dconc_dx=0
WQ Output face courant=0
WQ Output face peclet=0
WQ Output face adv mass=0
WQ Output face disp mass=0
WQ Output cell mass=0
WQ Output cell source sink temp=0
WQ Output nsm pathways=0
WQ Output nsm derived pathways=0
WQ Output MaxMinRange=-1
WQ Daily Max Min Mean=-1
WQ Daily Range=0
WQ Daily Time=0
WQ Create Restart=0
WQ Fixed Restart=0
WQ System Summary=0
WQ Write To DSS=0
WQ Use Fixed Temperature=0
Sorting and Armoring Iterations= 10
XS Update Threshold= 0.02
Bed Roughness Predictor= 0
Hydraulics Update Threshold= 0.02
Energy Slope Method= 1
Volume Change Method= 1
Sediment Retention Method= 0
XS Weighting Method= 0
Number of US Weighted Cross Sections= 1
Number of DS Weighted Cross Sections= 1
Upstream XS Weight=0
Main XS Weight=1
Downstream XS Weight=0
Number of DS XS's Weighted with US Boundary= 1
Upstream Boundary Weight= 1
Weight of XSs Associated with US Boundary= 0
Number of US XS's Weighted with DS Boundary= 1
Downstream Boundary Weight= 0.5
Weight of XSs Associated with DS Boundary= 0.5
Percentile Method= 0
Sediment Output Level= 3
Mass or Volume Output= 0
Output Increment Type= 1
Profile and TS Output Increment= 1
XS Output Flag= 0
XS Output Increment= 10
Write Gradation File= 0
Read Gradation Hotstart= 0
Write HDF5 File= 1
Write Binary Output= 1
Write DSS Sediment File= 0
SV Curve= 0
Specific Gage Flag= 0

--- SPICELKCK.f01 (steady flow) ---

Flow Title=Flows
Program Version=5.07
Number of Profiles= 6
Profile Names=01pct,10pct,04pct,02pct,0_2pct,01plus
River Rch & RM=SPICELKCK,Main            ,4059
     551     291     387     467     771     815
River Rch & RM=SPICELKCK,Main            ,1472
     621     329     437     526     867     919
Boundary for River Rch & Prof#=SPICELKCK,Main            , 1
Up Type= 0
Dn Type= 3
Dn Slope=0.05184
Boundary for River Rch & Prof#=SPICELKCK,Main            , 2
Up Type= 0
Dn Type= 3
Dn Slope=0.05184
Boundary for River Rch & Prof#=SPICELKCK,Main            , 3
Up Type= 0
Dn Type= 3
Dn Slope=0.05184
Boundary for River Rch & Prof#=SPICELKCK,Main            , 4
Up Type= 0
Dn Type= 3
Dn Slope=0.05184
Boundary for River Rch & Prof#=SPICELKCK,Main            , 5
Up Type= 0
Dn Type= 3
Dn Slope=0.05184
Boundary for River Rch & Prof#=SPICELKCK,Main            , 6
Up Type= 0
Dn Type= 3
Dn Slope=0.05184
DSS Import GetInterval= 0
DSS Import GetPeak= 0
DSS Import FillOption= 0

--- SPICELKCK.g01 (geometry) ---

Geom Title=Geometry
Program Version=5.07

River Reach=SPICELKCK       ,Main
Reach XY= 30
1958128.52531241230926.114431833 1958212.1507189230914.424746056
     1958328.087      230793.359     1958446.432       230770.56
     1958573.579      230618.367     1958622.948       230582.95
     1958691.635      230570.071     1958736.711      230529.288
     1958828.395      230291.671     1958951.359      230151.508
     1958969.604      229951.885     1959097.734      229826.549
     1959081.221      229731.871     1959091.953      229673.916
     1959303.382      229545.127     1959358.117      229481.806
     1959466.514      229285.403     1959585.234      229209.622
     1959582.424      229077.195     1959712.901       229050.41
     1959834.713      228964.049     1959901.176      228815.325
     1959963.359      228756.758     1960213.489      228709.074
     1960234.953      228652.192     1960219.869      228534.883
      1960232.89      228462.487     1960318.666      228322.708
     1960306.067      228214.049     1960380.691      228105.654

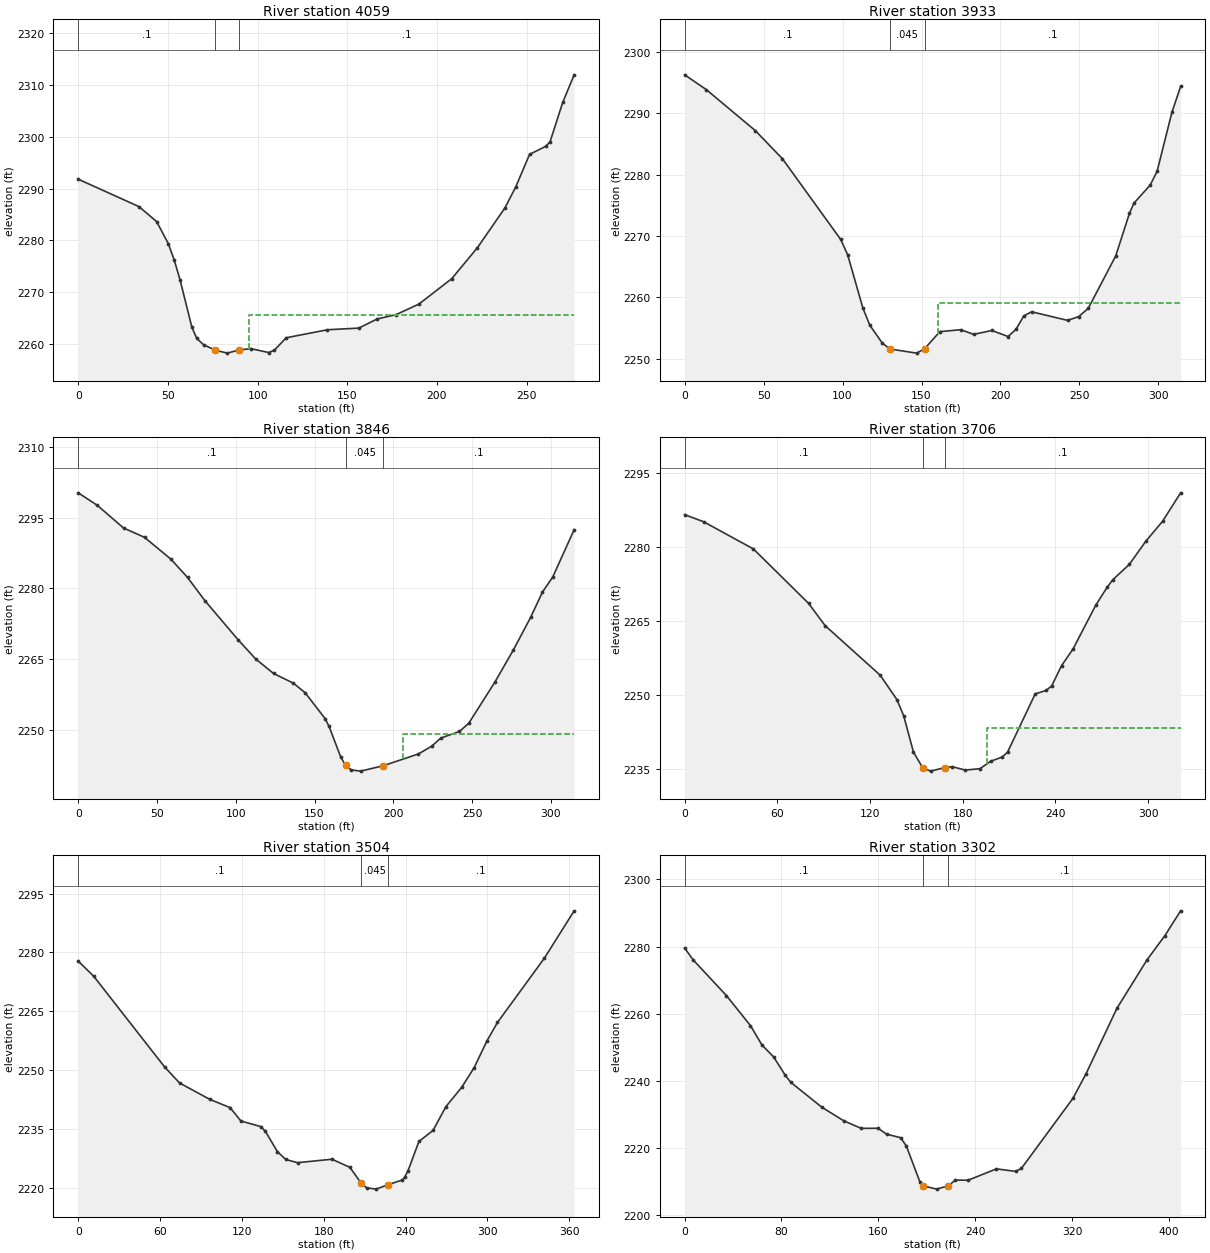
Type RM Length L Ch R = 1 ,4059    ,131.6,126.1,113.7
XS GIS Cut Line= 3
1958136.57760262231011.2510872931958143.52204707230855.001087293
1958080.32760265230752.917753965
#Sta/Elev= 30
       0 2291.81    33.8 2286.53    43.7 2283.64    50.2 2279.39    53.5 2276.24
    56.8 2272.34    63.4 2263.19    66.1 2261.08    69.9 2259.85    76.5 2258.81
    83.1 2258.24    89.6 2258.84    96.2 2259.11   106.1 2258.36   109.3 2258.78
   115.9  2261.2   138.9 2262.75   156.4 2263.07   166.7 2264.84   177.2 2265.67
   189.9  2267.7   208.2  2272.6   222.5 2278.57   237.8 2286.22   243.9 2290.31
   251.6 2296.59   260.6 2298.15     263    2299   270.1 2306.63276.4648 2311.95
#Mann= 3 ,-1 , 0
       0      .1       0    76.5    .045       0    89.6      .1       0
#XS Ineff= 2 , 0
                           95.25         2265.57
Permanent Ineff=
       F       F
Bank Sta=76.5,89.6
XS Rating Curve= 0 ,0
Exp/Cntr(USF)=0,0
Exp/Cntr=0.3,0.1

Type RM Length L Ch R = 1 ,3933    ,81.7,87.2,83.6
XS GIS Cut Line= 3
1958309.68225444230999.5210609691958229.90246361230846.013739302
1958136.91774189 230739.82408668
#Sta/Elev= 30
       0 2296.28    13.8 2293.85    44.8 2287.17    61.9  2282.6    98.8 2269.45
   103.2 2266.96   112.9 2258.23   117.3 2255.44   125.1 2252.57     130 2251.58
   146.9 2250.91   151.9 2251.61   161.6 2254.41   174.9 2254.73     183 2253.97
   194.5  2254.6   204.8 2253.62   209.8 2254.78   214.8 2256.98   219.7 2257.65
   242.5 2256.25   249.6 2256.87   255.6 2258.21     273 2266.76   281.7  2273.7
   284.5 2275.35   294.8 2278.29   299.2 2280.54   308.6 2290.18   314.1 2294.38
#Mann= 3 ,-1 , 0
       0      .1       0     130    .045       0   151.9      .1       0
#XS Ineff= 2 , 0
                          160.23         2259.06
Permanent Ineff=
       F       F
Bank Sta=130,151.9
XS Rating Curve= 0 ,0
Exp/Cntr(USF)=0,0
Exp/Cntr=0.3,0.1

Type RM Length L Ch R = 1 ,3846    ,139.8,139.8,139.7
XS GIS Cut Line= 4
 1958371.6452523230975.3786241811958321.80219961230864.062473168
1958252.02192584230696.2575291031958245.04478829230687.611945623
#Sta/Elev= 30
       0 2300.24    12.1  2297.6    28.8 2292.79    42.1 2290.82    58.8 2286.21
    69.4 2282.33    80.4 2277.42   101.7 2269.05   112.7 2265.06     124    2262
   136.6 2259.95   144.1 2257.91   156.7 2252.45   159.2 2250.81   166.7 2244.28
   169.7 2242.54   173.2 2241.59   179.3 2241.33   193.7 2242.48   215.9 2244.96
   224.4 2246.61   230.1 2248.32     242 2249.73   247.9 2251.46   264.6 2260.23
   276.3 2267.03   287.2 2273.89   294.7 2279.24   301.2 2282.41   314.8 2292.44
#Mann= 3 ,-1 , 0
       0      .1       0   169.7    .045       0   193.7      .1       0
#XS Ineff= 2 , 0
                          206.38         2249.09
Permanent Ineff=
       F       F
Bank Sta=169.7,193.7
XS Rating Curve= 0 ,0
Exp/Cntr(USF)=0,0
Exp/Cntr=0.3,0.1

Type RM Length L Ch R = 1 ,3706    ,206.5,201.8,194
XS GIS Cut Line= 4
1958495.51434123230923.1784859491958449.60069551230816.340964159
1958372.78363438230640.6329737781958365.97252174230629.650054644
#Sta/Elev= 30
       0  2286.6    12.3 2285.16    44.5 2279.65    80.2 2268.64    90.9 2264.13
   126.6 2254.08   137.4 2249.14   141.8 2245.84   148.1  2238.5   154.2 2235.29
   159.2 2234.67   168.32235.387   173.2 2235.57   181.6 2234.88   191.1 2235.17
   198.2 2236.69   205.4  2237.5     209 2238.52   226.9 2250.32     234 2251.01
   237.6 2251.95   243.9 2256.01   251.4 2259.42     266 2268.23   273.4 2271.88
     277 2273.39   287.8 2276.53   298.5 2281.23   309.3 2285.25     321 2291.02
#Mann= 3 ,-1 , 0
       0      .1       0   154.2    .045       0   168.3      .1       0
#XS Ineff= 2 , 0
                          195.56          2243.4
Permanent Ineff=
       F       F
Bank Sta=154.2,168.3
XS Rating Curve= 0 ,0
Exp/Cntr(USF)=0,0
Exp/Cntr=0.3,0.1

Type RM Length L Ch R = 1 ,3504    ,201.8,202.4,201.8
XS GIS Cut Line= 4
1958674.75415052230813.6920999831958602.35186302230675.068208074
1958505.22684321 230570.879550461958465.57173654 230519.68841276
#Sta/Elev= 30
       0 2277.79    11.4 2273.92    63.3 2250.83    74.3 2246.73    96.5 2242.55
   111.3 2240.46   119.3 2237.04   133.9 2235.61   137.2 2234.42     146 2229.26
   152.1 2227.24   160.8 2226.42     186  2227.3   199.2 2225.23   207.32221.264
   211.5 2220.01   218.4 2219.68   227.3 2220.82   237.7 2222.02   239.3 2222.73
   241.7 2224.27   249.8 2231.83   260.2 2234.66   269.5 2240.66   281.1 2245.61
   290.2 2250.58   299.7 2257.48   307.4 2262.16   341.8 2278.55   363.6  2290.6
#Mann= 3 ,-1 , 0
       0      .1       0   207.3    .045       0   227.3      .1       0
Bank Sta=207.3,227.3
XS Rating Curve= 0 ,0
Exp/Cntr(USF)=0,0
Exp/Cntr=0.3,0.1

Type RM Length L Ch R = 1 ,3302    ,182.3,174.4,166.4
XS GIS Cut Line= 4
1958872.53600904230687.4295742311958770.11326087230577.060233539
1958644.73368985230440.2022510811958589.57532076230391.457645838
#Sta/Elev= 30
       0 2279.54     7.1 2275.98    34.5 2265.38    54.3 2256.45    63.9 2250.61
    73.6 2247.05    83.2 2241.56    87.7  2239.5   113.4 2232.07   131.5 2228.02
   145.9 2225.78   159.8 2225.81   166.8 2224.05   178.4    2223   183.1 2220.57
   194.5 2209.71     197 2208.66   208.2 2207.66   217.9 2208.66   223.6 2210.35
   234.2 2210.32   257.6  2213.7   273.6 2212.95   278.3 2213.87   320.8 2234.72
   331.7 2242.11   357.2  2261.6     382    2276   396.8 2283.26   409.8 2290.65
#Mann= 3 ,-1 , 0
       0      .1       0     197    .045       0   217.9      .1       0
Bank Sta=197,217.9
XS Rating Curve= 0 ,0
Exp/Cntr(USF)=0,0
Exp/Cntr=0.3,0.1

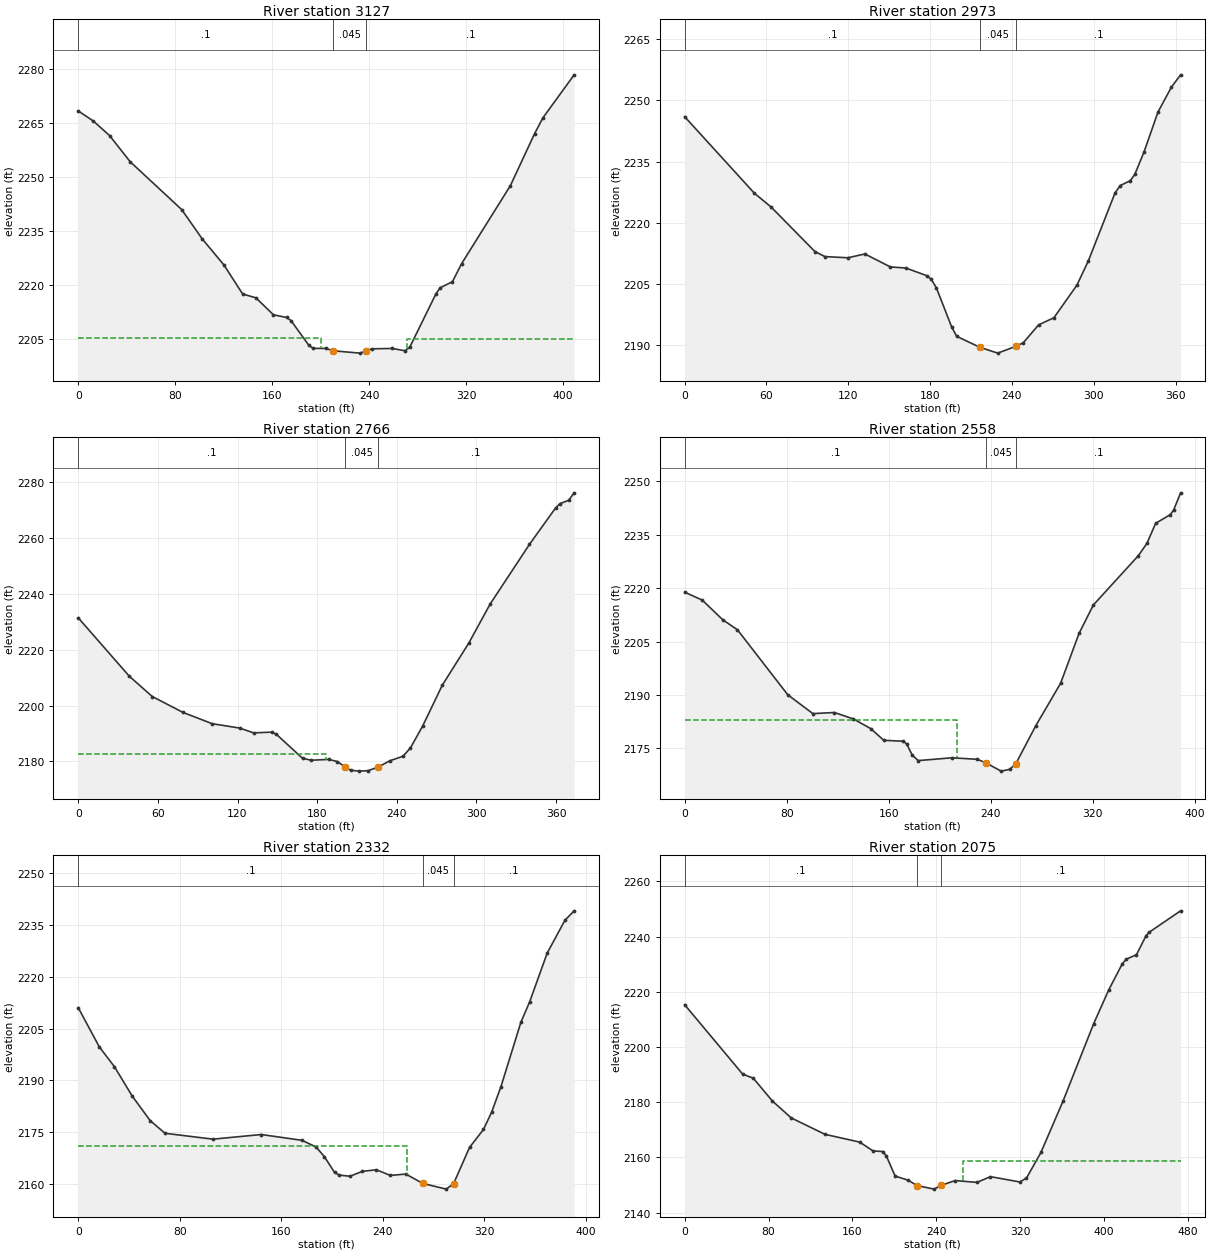
Type RM Length L Ch R = 1 ,3127    ,151.1,153.9,154.3
XS GIS Cut Line= 4
1958993.38211019230502.5734946291958891.64247103230419.001648179
 1958745.0889432230349.9640358941958633.51935757  230320.8883257
#Sta/Elev= 30
       0 2268.24    12.5  2265.4    25.9 2261.37    42.8 2254.13    85.3 2240.83
   102.3 2232.66   120.2 2225.42   135.6 2217.37   146.5 2216.31     161 2211.59
   171.9 2210.84   175.5 2209.98     190 2203.21   193.6 2202.27   204.5 2202.24
   210.2 2201.59   232.4 2200.94   237.7 2201.58   242.3 2202.14   258.9 2202.24
   269.4  2201.6   273.4 2202.58   295.1 2217.46   298.5 2219.09   308.6 2220.78
   316.2  2225.8   356.4 2247.46   376.4 2261.93   383.2 2266.29     409 2278.25
#Mann= 3 ,-1 , 0
       0      .1       0   210.2    .045       0   237.7      .1       0
#XS Ineff= 2 , 0
           199.9 2205.17  271.03         2204.99
Permanent Ineff=
       F       F
Bank Sta=210.2,237.7
XS Rating Curve= 0 ,0
Exp/Cntr(USF)=0,0
Exp/Cntr=0.3,0.1

Type RM Length L Ch R = 1 ,2973    ,214,207.4,196.7
XS GIS Cut Line= 4
1959068.47565338230347.5416635331958946.14584915230285.771168331
1958781.42452861230194.9322047991958743.71522444230186.747239553
#Sta/Elev= 30
       0 2246.01    51.2 2227.21    63.4 2223.85    95.5 2212.93   102.8 2211.69
   119.6  2211.4   132.2 2212.33   150.9 2209.14   162.1 2208.89   177.8 2206.98
   180.9  2206.1   184.6 2204.01   195.8 2194.42   199.5 2192.12   216.6 2189.41
   229.6    2188     243 2189.69   248.3 2190.54   259.5 2194.92   270.8 2196.69
   287.7 2204.71   296.1 2210.69   315.7 2227.39   319.5 2229.13   326.8 2230.32
   330.1 2231.86   336.9 2237.39   347.1 2247.16     357  2253.3   363.7 2256.29
#Mann= 3 ,-1 , 0
       0      .1       0   216.6    .045       0     243      .1       0
Bank Sta=216.6,243
XS Rating Curve= 0 ,0
Exp/Cntr(USF)=0,0
Exp/Cntr=0.3,0.1

Type RM Length L Ch R = 1 ,2766    ,195.6,208.1,222.9
XS GIS Cut Line= 4
1959173.84885107230125.894592514 1959035.7736265230078.658331477
1958888.00891249230067.7576558541958808.51036305230068.284136314
#Sta/Elev= 30
       0 2231.42    38.5  2210.5    55.8 2203.23    78.9 2197.55   100.9 2193.51
   121.7 2191.93   132.1 2190.22     146 2190.48   149.3  2189.7     169  2181.1
   175.6 2180.42   188.7 2180.72   195.3 2179.94   201.2 2177.97   205.2 2176.83
   211.8 2176.52   218.4 2176.69   225.8 2177.94   234.8 2180.24   244.7 2181.85
   250.3 2184.85   259.5 2192.69   274.3 2207.32   294.1 2222.26   310.4 2236.41
   339.9 2257.69   359.6 2270.75   362.9 2272.28   369.5 2273.52   373.6 2276.17
#Mann= 3 ,-1 , 0
       0      .1       0   201.2    .045       0   225.8      .1       0
#XS Ineff= 2 , 0
          186.73 2182.53
Permanent Ineff=
       F       F
Bank Sta=201.2,225.8
XS Rating Curve= 0 ,0
Exp/Cntr(USF)=0,0
Exp/Cntr=0.3,0.1

Type RM Length L Ch R = 1 ,2558    ,229.2,226.5,217.7
XS GIS Cut Line= 4
1959221.08511211230036.2668151621959093.91056317229951.483782532
1958987.32617929229853.3777019171958902.67000857229819.647508898
#Sta/Elev= 30
       0 2218.89    13.8 2216.65    29.8 2211.14    41.4  2208.3    80.8 2190.05
   100.5 2184.75   117.4 2185.06   132.1 2183.27   145.8 2180.55   156.1 2177.24
   171.4 2176.99     174 2176.24   178.4 2173.09   183.1 2171.54   209.6 2172.33
   229.5  2171.9   236.4 2170.85   248.1 2168.58     255  2169.1   259.7 2170.72
   275.3 2181.38   294.7 2193.26   309.2 2207.31   320.4 2215.29   355.7 2229.16
   362.4  2232.6   369.2 2238.23   380.8  2240.7   383.3 2241.97   388.8 2246.81
#Mann= 3 ,-1 , 0
       0      .1       0   236.4    .045       0   259.7      .1       0
#XS Ineff= 2 , 0
          213.47 2182.87
Permanent Ineff=
       F       F
Bank Sta=236.4,259.7
XS Rating Curve= 0 ,0
Exp/Cntr(USF)=0,0
Exp/Cntr=0.3,0.1

Type RM Length L Ch R = 1 ,2332    ,244.8,256.6,267
XS GIS Cut Line= 4
1959321.61356509229848.5329571951959175.06003725229746.793318039
1959022.45057852229670.4885886721958982.99606303229656.034954283
#Sta/Elev= 30
       0 2211.03    16.7 2199.66    28.5 2194.01    42.5 2185.54    56.7 2178.42
    68.4 2174.75   106.2 2173.05   144.3 2174.39   176.3 2172.72   187.5 2170.81
     194 2168.04   202.1 2163.45   205.8 2162.67   214.3 2162.34   224.1 2163.76
   235.1 2164.21   246.1 2162.58   258.3 2162.97   271.8 2160.25   290.2 2158.62
  295.95  2160.2   308.5 2170.65   319.5 2175.85     326 2180.89   333.3 2188.23
     349  2206.8   355.9 2212.69   369.8 2226.83   383.8  2236.3     391 2238.99
#Mann= 3 ,-1 , 0
       0      .1       0   271.8    .045       0  295.95      .1       0
#XS Ineff= 2 , 0
          259.31 2171.08
Permanent Ineff=
       F       F
Bank Sta=271.8,295.95
XS Rating Curve= 0 ,0
Exp/Cntr(USF)=0,0
Exp/Cntr=0.3,0.1

Type RM Length L Ch R = 1 ,2075    ,178,171.4,165.9
XS GIS Cut Line= 4
1959426.98676278229748.0045042191959343.41491633229630.519444717
 1959202.9173194229456.1086347351959112.22265726229403.060813483
#Sta/Elev= 30
       0  2215.3    55.3 2190.17    65.5 2188.67    83.6 2180.44   101.7 2174.28
   133.9 2168.34   167.1 2165.51   179.7 2162.32     189 2162.11   192.4 2160.52
   200.8 2153.22   213.5 2151.68   221.5 2149.78     238 2148.48     245 2149.89
   258.1 2151.58     279 2150.92   291.7    2153   319.7 2151.08   326.1 2152.45
   339.9 2161.76   360.9 2180.28   390.3  2208.5   404.7 2220.74   417.4 2230.04
   421.2 2231.78   431.1 2233.45   440.2 2240.31   443.1 2241.56   473.2 2249.34
#Mann= 3 ,-1 , 0
       0      .1       0   221.5    .045       0     245      .1       0
#XS Ineff= 2 , 0
                          265.62         2158.54
Permanent Ineff=
       F       F
Bank Sta=221.5,245
XS Rating Curve= 0 ,0
Exp/Cntr(USF)=0,0
Exp/Cntr=0.3,0.1

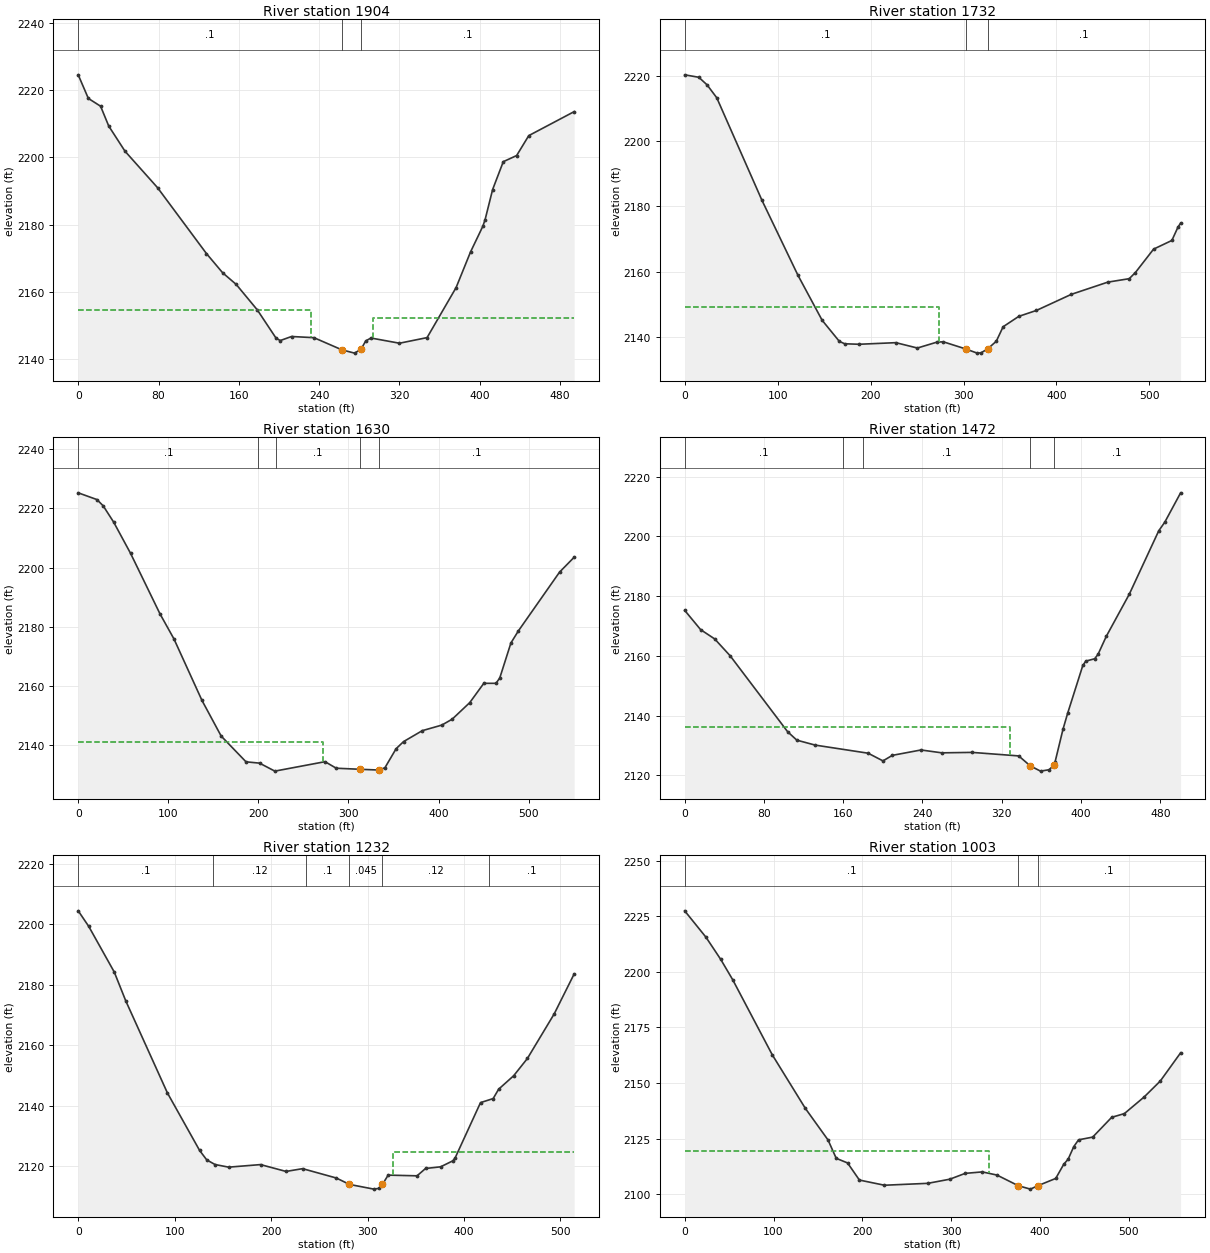
Type RM Length L Ch R = 1 ,1904    ,170.9,171.3,170.6
XS GIS Cut Line= 4
 1959568.6955459229620.829955274 1959469.3782791229483.965916885
1959304.65695856229364.0584850221959194.84990762229312.815194583
#Sta/Elev= 30
       0 2224.57    10.1 2217.54    22.3 2215.22    30.4 2209.32    46.6 2201.83
      79 2190.98   127.7 2171.37   143.9 2165.62   157.3 2162.19   178.4 2154.58
   197.2 2146.11   201.3 2145.46   212.5 2146.66   234.8 2146.31   262.82142.673
   275.3 2141.71   281.7 2142.88   286.4 2145.35   291.6 2146.21     320 2144.66
   347.5 2146.33   376.4 2161.22   390.8 2171.85     403 2179.45   405.3 2181.46
   412.8 2190.42   423.4 2198.71   436.7 2200.53   448.8 2206.47     494 2213.61
#Mann= 3 ,-1 , 0
       0      .1       0   262.8    .045       0   281.7      .1       0
#XS Ineff= 2 , 0
          232.09 2154.57  293.98         2152.14
Permanent Ineff=
       F       F
Bank Sta=262.8,281.7
XS Rating Curve= 0 ,0
Exp/Cntr(USF)=0,0
Exp/Cntr=0.3,0.1

Type RM Length L Ch R = 1 ,1732    ,99.9,102.1,101.9
XS GIS Cut Line= 4
1959696.61664136229502.4452573421959523.40804489229313.283237521
1959400.33877898229228.9579997691959272.45973774229227.653111593
#Sta/Elev= 30
       0 2220.24    15.2 2219.49    24.1 2217.17    34.5 2213.23    83.2 2181.82
   121.9 2158.91   147.9 2145.16   166.4 2138.71   172.2 2137.97   187.7 2137.82
   227.2 2138.31   250.4 2136.67   271.6 2138.49   278.3 2138.57   302.8 2136.35
   314.7 2135.11   318.9 2135.21   325.9 2136.39   335.3 2138.75   342.6 2143.17
   359.5 2146.36   378.4 2148.16     416 2153.09   455.3 2156.83   478.3 2157.88
   484.9 2159.75   504.5 2166.92   524.2 2169.58   530.8 2173.69   533.6 2174.87
#Mann= 3 ,-1 , 0
       0      .1       0   302.8    .045       0   325.9      .1       0
#XS Ineff= 2 , 0
          273.78 2149.14
Permanent Ineff=
       F       F
Bank Sta=302.8,325.9
XS Rating Curve= 0 ,0
Exp/Cntr(USF)=0,0
Exp/Cntr=0.3,0.1

Type RM Length L Ch R = 1 ,1630    ,148.5,157.7,155.9
XS GIS Cut Line= 4
1959772.74982333229452.8089572211959631.44476894229281.897129536
1959468.60751579  229155.39546181959393.38265002229058.543447118
#Sta/Elev= 30
       0 2225.24    20.8 2222.96    27.8 2220.82    39.4 2215.32    58.1 2204.81
    90.8 2184.35   106.3 2175.89   137.4 2155.12   158.7 2143.09   186.3 2134.38
   201.3 2133.94   218.3 2131.24     274 2134.43   286.5 2132.22   312.4 2131.87
   333.4 2131.61   340.5 2132.37   352.9  2138.8   361.2 2141.21     382 2144.91
   403.6 2146.78   415.2 2148.79   434.7 2154.38   450.3  2160.9   463.8  2160.9
     468 2162.69   480.4 2174.53   488.7 2178.61   534.4 2198.46   550.6 2203.48
#Mann= 5 ,-1 , 0
       0      .1       0     200     .12       0     220      .1       0
   312.4    .045       0   333.4      .1       0
#XS Ineff= 2 , 0
          271.78 2141.19
Permanent Ineff=
       F       F
Bank Sta=312.4,333.4
XS Rating Curve= 0 ,0
Exp/Cntr(USF)=0,0
Exp/Cntr=0.3,0.1

Type RM Length L Ch R = 1 ,1472    ,243.2,240.5,242.3
XS GIS Cut Line= 4
1959847.26836739229325.3005272481959660.74569561229144.833786364
 1959531.1487743229053.9948228321959460.79144484229010.440285543
#Sta/Elev= 30
       0 2175.26    16.1  2168.8    30.3 2165.69    45.9 2160.05   103.9 2134.64
   113.2 2131.82   131.7 2130.17   185.1 2127.46   200.1 2124.89   209.6 2126.74
   238.5 2128.54   259.5 2127.58     290 2127.73   337.1 2126.55   348.8 2123.21
   359.1 2121.46   367.7 2121.92   372.4 2123.39   373.7  2124.4   381.8 2135.47
   386.5 2140.83   401.8 2156.82   404.8 2158.27   413.8 2159.06   417.2 2160.57
   425.5 2166.57   448.7 2180.66   478.4 2201.86   484.6 2204.81   500.5 2214.58
#Mann= 5 ,-1 , 0
       0      .1       0     160     .12       0     180      .1       0
   348.8    .045       0   372.4      .1       0
#XS Ineff= 2 , 0
          328.37 2136.16
Permanent Ineff=
       F       F
Bank Sta=348.8,372.4
XS Rating Curve= 0 ,0
Exp/Cntr(USF)=0,0
Exp/Cntr=0.3,0.1

Type RM Length L Ch R = 1 ,1232    ,229.8,228.9,227.1
XS GIS Cut Line= 4
1959999.87782613229200.548350664  1959871.492091229066.106684636
1959688.60297776228903.8077364581959618.84701104 228857.13278814
#Sta/Elev= 30
       0 2204.51    10.9 2199.36    37.4 2184.22    49.3 2174.69    92.5 2144.18
   125.9 2125.12   133.3 2121.99   141.9 2120.46     156 2119.59   189.1 2120.44
   215.5 2118.17   232.7 2119.09   267.6    2116   281.3 2113.87   306.6 2112.31
   311.8 2112.56   315.5 2113.85   321.4 2116.95   351.4 2116.72   360.2 2119.15
   375.8  2119.7   388.4 2121.67   390.8  2122.6   417.2 2140.97   430.3 2142.31
     436 2145.42   451.6 2149.88   465.8 2155.59   493.6 2170.36   514.3  2183.6
#Mann= 6 ,-1 , 0
       0      .1       0     140     .12       0   235.9      .1       0
   281.3    .045       0   315.5     .12       0   425.9      .1       0
#XS Ineff= 2 , 0
                          326.93         2124.64
Permanent Ineff=
       F       F
Bank Sta=281.3,315.5
XS Rating Curve= 0 ,0
Exp/Cntr(USF)=0,0
Exp/Cntr=0.3,0.1

Type RM Length L Ch R = 1 ,1003    ,361.9,360.7,356.9
XS GIS Cut Line= 4
1960198.51235972229064.8954984551959991.39952287228877.161640488
1959833.94531941228753.6206500841959767.75240871228711.165886671
#Sta/Elev= 30
       0 2227.45      24 2215.56    40.6 2205.59      54  2196.5    98.6 2162.68
   135.8  2138.6   161.4 2124.35   170.6 2116.11   183.4 2114.02   196.7 2106.33
   224.9    2104   273.8 2104.86   298.5 2106.72   315.8 2109.34     335    2110
   351.6 2108.57   375.6 2103.78   389.2 2102.25   397.5 2103.77   417.7 2107.06
   426.7 2113.41   431.7 2115.73     438 2121.35   443.4 2124.43   459.3 2125.65
   480.7 2134.55     495 2136.23   517.2 2143.69   535.4 2150.87   558.3 2163.58
#Mann= 3 ,-1 , 0
       0      .1       0   375.6    .045       0   397.5      .1       0
#XS Ineff= 2 , 0
          342.98 2119.47
Permanent Ineff=
       F       F
Bank Sta=375.6,397.5
XS Rating Curve= 0 ,0
Exp/Cntr(USF)=0,0
Exp/Cntr=0.3,0.1

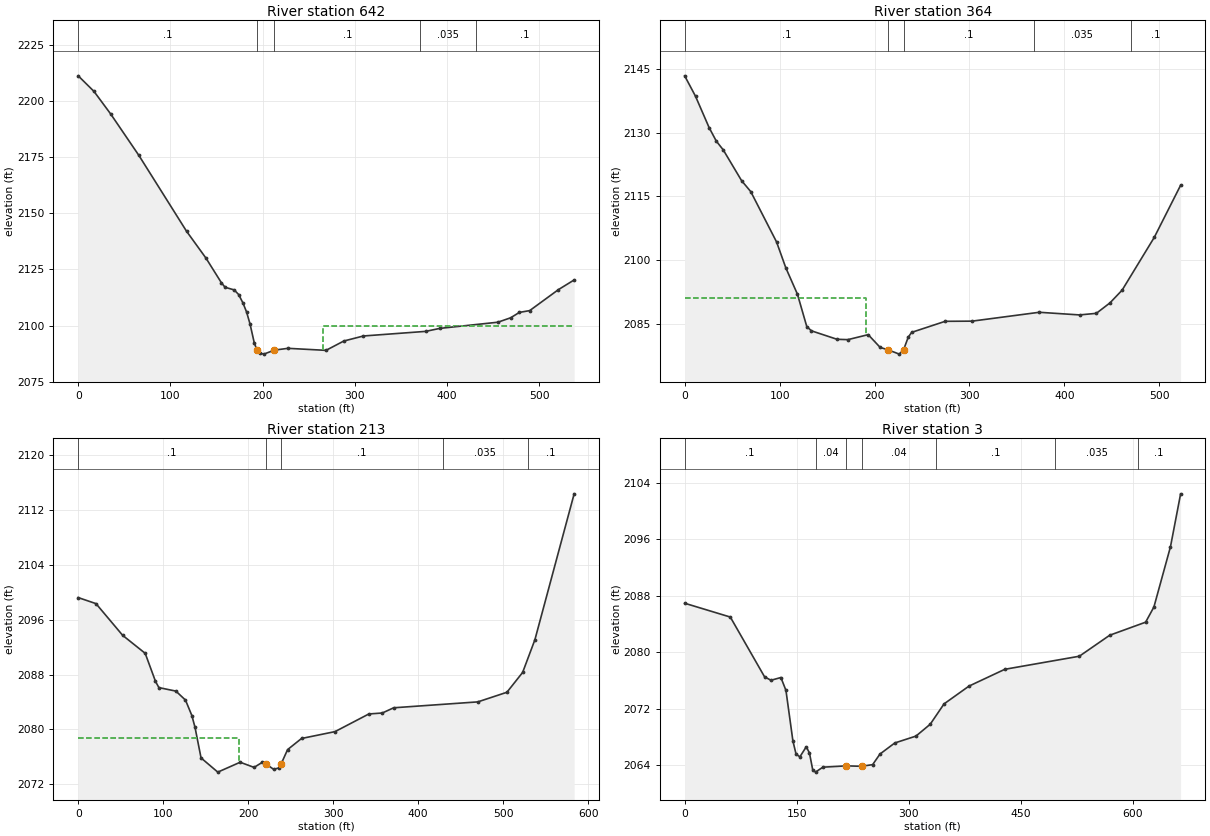
Type RM Length L Ch R = 1 ,642     ,278.4,278.4,273.7
XS GIS Cut Line= 4
1960394.72452095228808.1240282041960256.64929638228707.595575228
1960015.62324647228575.5762815611959928.38372437228546.496440861
#Sta/Elev= 30
       0 2211.43    17.1 2204.48    35.2  2194.4    65.7 2175.95   117.4 2142.09
   138.6 2130.01   155.1 2119.16   159.2 2117.06   169.1 2115.89   173.9 2113.83
   178.6 2110.05   182.5 2106.04   186.3 2100.61   190.8 2092.34   193.8 2089.04
   197.5 2087.62   201.2 2087.23   212.7 2089.02   227.4 2089.82   268.6 2088.91
   287.9 2093.08   309.2 2095.33   376.6 2097.38     392 2098.72   454.9 2101.47
   468.7 2103.44   478.2 2105.85   489.4 2106.65   520.6 2116.03   537.6 2120.34
#Mann= 5 ,-1 , 0
       0      .1       0   193.8    .045       0   212.7      .1       0
  370.79    .035       0  430.79      .1       0
#XS Ineff= 2 , 0
                             265         2099.87
Permanent Ineff=
       F       F
Bank Sta=193.8,212.7
XS Rating Curve= 0 ,0
Exp/Cntr(USF)=0,0
Exp/Cntr=0.3,0.1

Type RM Length L Ch R = 1 ,364     ,158.3,151.3,146.8
XS GIS Cut Line= 4
1960459.95246257228518.1687149041960318.73047994228448.388441135
1960037.94794978228335.4108550311959975.72275266228336.269133612
#Sta/Elev= 30
       0  2143.3    11.4 2138.51    25.7 2131.17    33.3 2127.98    40.6 2125.93
      60 2118.68    69.6 2116.13    96.8 2104.31   106.5 2098.26   118.8 2092.04
   128.6 2084.47   133.5 2083.46   160.5 2081.47   171.9 2081.39   193.3 2082.56
   205.9 2079.57   214.3 2078.99   226.1 2077.99  230.57 2079.01   235.5 2081.97
   239.1  2083.1   274.4 2085.69   302.7 2085.73   373.5 2087.81   415.9 2087.19
   433.6 2087.56     448 2090.02   460.8 2093.01   494.6 2105.37   522.4 2117.62
#Mann= 5 ,-1 , 0
       0      .1       0   214.3    .045       0  230.57      .1       0
  367.52    .035       0  470.18      .1       0
#XS Ineff= 2 , 0
           191.4 2091.21
Permanent Ineff=
       F       F
Bank Sta=214.3,230.57
XS Rating Curve= 0 ,0
Exp/Cntr(USF)=0,0
Exp/Cntr=0.3,0.1

Type RM Length L Ch R = 1 ,213     ,191.7,209.6,207.4
XS GIS Cut Line= 4
1960537.14287943228362.7413948211960413.33273654228294.107511262
1960206.42861943228286.507012125 1959972.8491919228310.452829465
#Sta/Elev= 30
       0 2099.21    20.9 2098.33    52.3 2093.71    78.8 2091.09    90.9 2087.01
    94.9  2086.1   114.9 2085.59   126.2 2084.28   133.7 2082.03   137.4 2080.31
   144.5 2075.86   164.2 2073.79   190.5 2075.23   206.9 2074.48   216.7 2075.23
   220.7 2074.99   229.9  2074.2   236.3 2074.41  238.73 2074.99   246.3 2077.07
   262.7 2078.69   302.1 2079.69   341.9 2082.26   357.7  2082.4   371.1 2083.16
   470.1 2084.02   504.3 2085.42   522.8 2088.31   537.2 2093.06   583.4 2114.32
#Mann= 5 ,-1 , 0
       0      .1       0   220.7    .045       0  238.73      .1       0
   428.6    .035       0   528.6      .1       0
#XS Ineff= 2 , 0
          189.24 2078.76
Permanent Ineff=
       F       F
Bank Sta=220.7,238.73
XS Rating Curve= 0 ,0
Exp/Cntr(USF)=0,0
Exp/Cntr=0.3,0.1

Type RM Length L Ch R = 1 ,3       ,,,
XS GIS Cut Line= 6
1960536.20442903228250.7758443011960422.98977902228116.787073459
1960401.22890305228111.529319792 1960337.7104395228102.059567362
1960313.45578687228099.3050114051959978.39718836228273.442924466
#Sta/Elev= 30
       02086.938  61.1052084.978 106.9542076.504 115.5452076.012 128.8422076.402
 135.6032074.573 144.915  2067.4 149.1752065.524 154.2592065.156 162.7922066.578
 167.0872065.695 171.3822063.339  175.182062.983 184.9942063.684 216.6112063.872
 236.8622063.809  251.682064.048 261.508 2065.55 281.3222067.119 309.6792068.094
 328.7772069.776 347.264 2072.66 380.6382075.183 428.6092077.567 528.4412079.422
 569.113  2082.4  617.18 2084.25 628.2732086.402 650.457 2094.95 664.0422102.457
#Mann= 7 ,-1 , 0
       0      .1       0  175.42     .04       0 216.611    .045       0
 236.862     .04       0  336.43      .1       0  496.43    .035       0
  606.43      .1       0
Bank Sta=216.611,236.862
XS Rating Curve= 0 ,0
Exp/Cntr(USF)=0,0
Exp/Cntr=0.3,0.1
LCMann Table=0

Chan Stop Cuts=-1
Use User Specified Reach Order=0
Composite Channel Slope=5